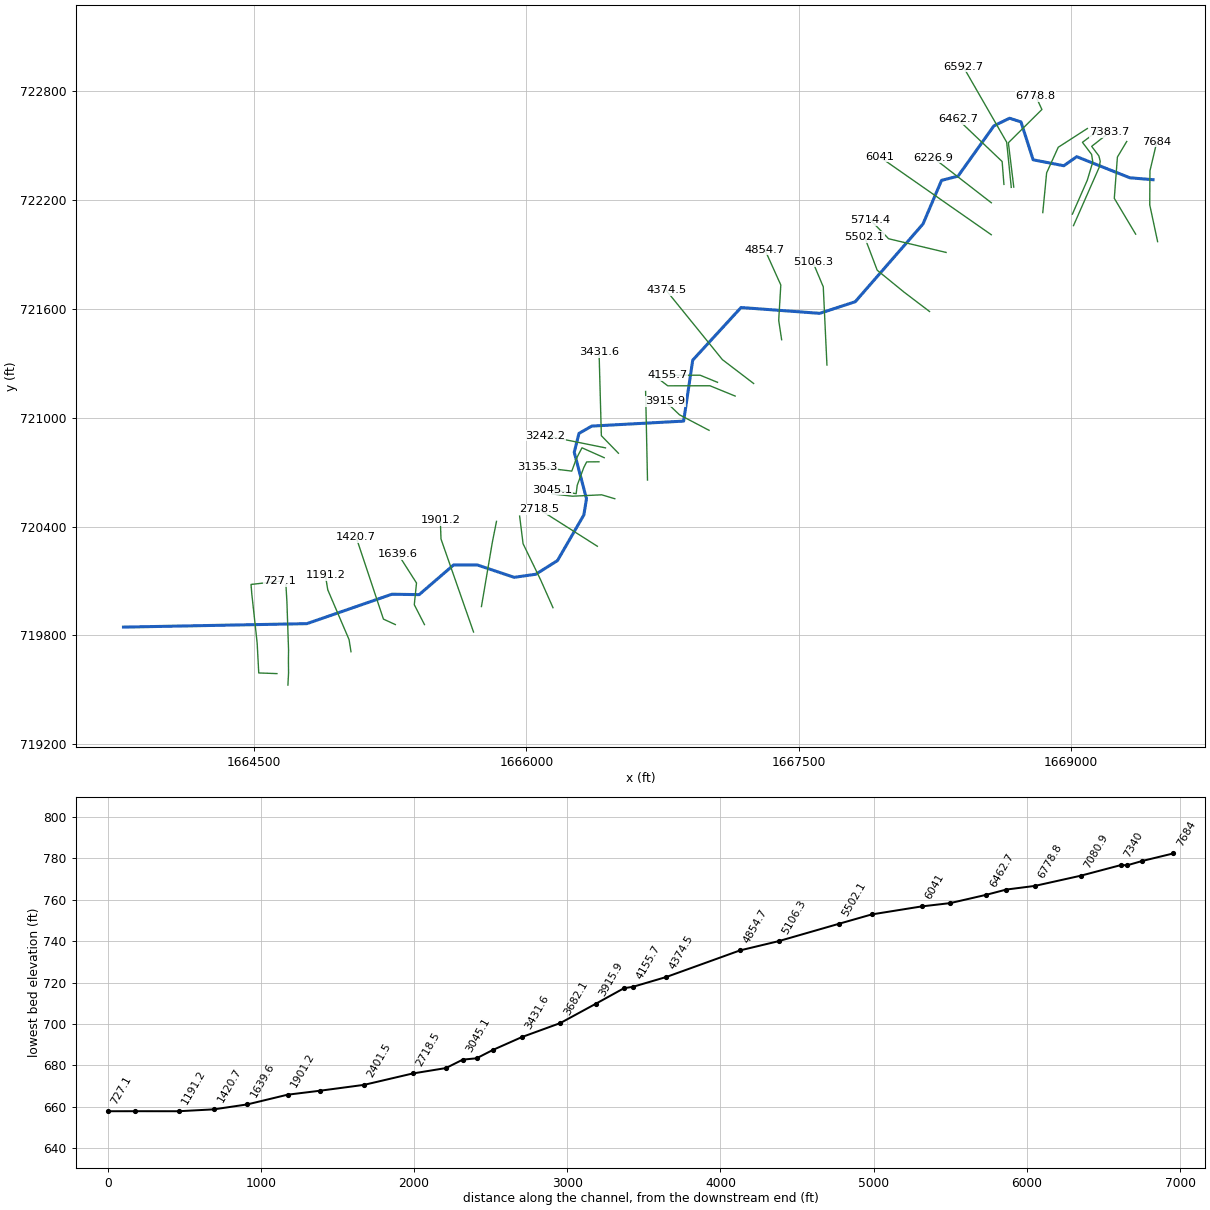
--- HOLBERTRUN.prj (project) ---

Proj Title=HOLBERTRUN
Current Plan=p01
Default Exp/Contr=0,0
English Units
Geom File=g01
Flow File=f01
Plan File=p01
BEGIN DESCRIPTION:
END DESCRIPTION:
DSS Export Rating Curves= 0
DSS Export Rating Curve Sorted= 0
DSS Export Volume Flow Curves= 0
DXF Filename=..\..\..\..\..\Engineering\Hydraulics\HOLBERTRUN\HOLBERTRUN.
DXF OffsetX= 0
DXF OffsetY= 0
DXF ScaleX= 0
DXF ScaleY= 0

--- HOLBERTRUN.p01 (plan) ---

Plan Title=Floodplain
Program Version=4.00
Geom File=g01
Flow File=f01
K Sum by GR=0
Std Step Tol=0.01
Critical Tol=0.01
Num of Std Step Trials=20
Max Error Tol=0.3
Flow Tol Ratio=0.001
Split Flow NTrial=30
Split Flow Tol=0.02
Split Flow Ratio=0.02
Log Output Level=0
Friction Slope Method=1
Unsteady Friction Slope Method=2
Unsteady Bridges Friction Slope Method=1
Global Log Level=0
CheckData=False
Run HTab=0
Run UNet=0
Run PostProcess=0
UNET Theta=0
UNET Theta Warmup=0
UNET ZTol=0
UNET ZSATol=0
UNET MxIter=0
UNET MaxInSteps=0
UNET DtIC=0
UNET DtMin=0
UNET MaxCRTS=0
UNET WFStab=0
UNET SFStab=0
UNET WFX=0
UNET SFX=0
UNET DSS MLevel=0
UNET DZMax Abort=0
UNET Convert EG Bridges=0
UNET Use Existing IB Tables=0
UNET Froude Limit=0
UNET Froude Power=0
Write IC File=0
Echo Input=False
Echo Output=False
Write Detailed=0

--- HOLBERTRUN.f01 (steady flow) ---

Flow Title=NFF Regression Equation
Program Version=4.10
Number of Profiles= 1
Profile Names=P100yr
River Rch & RM=HOLBERTRUN,Main            ,7684
971.1095
River Rch & RM=HOLBERTRUN,Main            ,7383.7
968.1162
River Rch & RM=HOLBERTRUN,Main            ,6592.7
1242.055
River Rch & RM=HOLBERTRUN,Main            ,4374.5
 1275.56
River Rch & RM=HOLBERTRUN,Main            ,1191.2
1415.231
Boundary for River Rch & Prof#=HOLBERTRUN,Main            , 1
Up Type= 0
Dn Type= 3
Dn Slope=0.001
DSS Import GetInterval= 0
DSS Import GetPeak= 0
DSS Import FillOption= 0

--- HOLBERTRUN.g01 (geometry) ---

Geom Title=2003 WVU SAMB 3 Meter DEM
Program Version=4.10

River Reach=HOLBERTRUN      ,Main
Reach XY= 30
     1669453.779      722311.886     1669325.328      722322.766
     1669033.315       722438.98     1668962.134       722388.98
     1668792.988      722421.738     1668726.023      722630.502
     1668663.158      722650.834     1668577.065      722609.148
     1668378.874       722331.48     1668288.168      722308.277
     1668186.145      722068.168     1667812.547      721639.472
     1667616.821      721575.408      1667183.01       721607.52
     1666916.714      721317.424     1666866.722      720981.399
     1666360.368      720954.008     1666289.677       720913.59
     1666263.592      720810.002     1666331.153      720553.672
     1666316.616      720464.215     1666171.187      720212.649
     1666052.046      720137.389     1665932.537      720120.245
      1665730.06      720188.379     1665598.981      720188.799
     1665408.854      720024.903     1665258.984      720027.276
     1664789.904      719865.047      1663779.09      719845.936

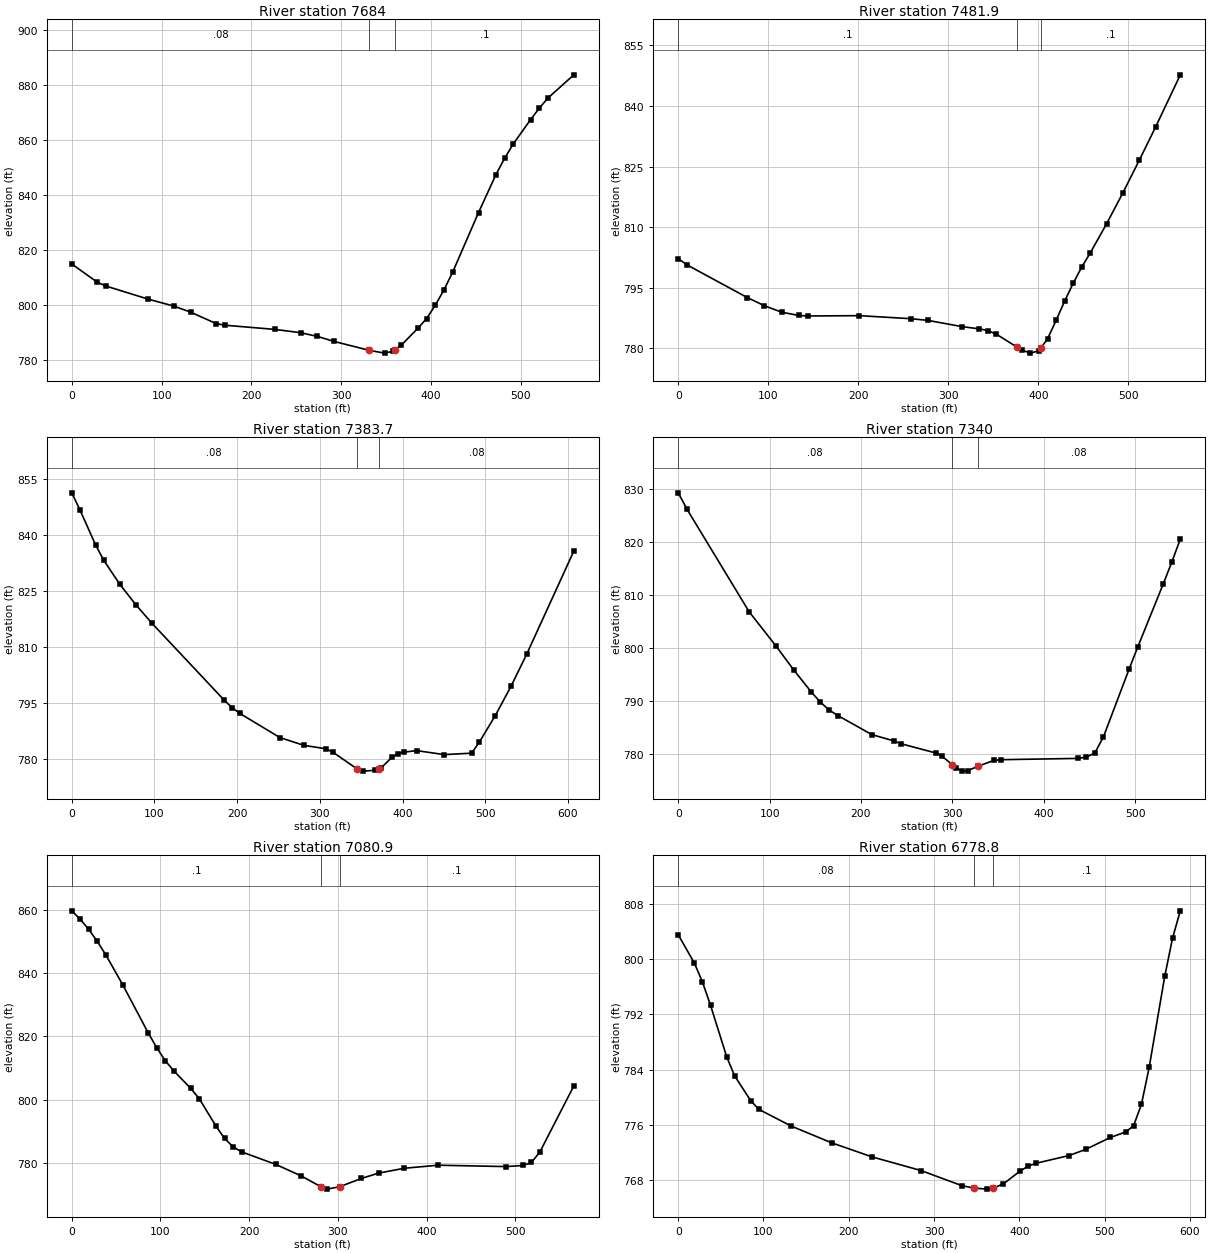
Type RM Length L Ch R = 1 ,7684    ,202.5,202.1,199.4
XS GIS Cut Line= 4
      1669479.14      721970.518     1669435.676      722173.802
     1669436.933      722360.948     1669474.748      722520.352
#Sta/Elev= 30
       0  814.84    28.4   808.2    37.8  806.85      85  802.06   113.4  799.56
   132.3  797.34   160.6  793.19   170.1   792.6   226.6  791.05   254.7  789.87
   273.4  788.53   292.1  786.69   331.1783.4655   348.2  782.45   357.6  783.13
   360.1783.7364     367  785.41   385.7  791.62     395     795   404.7  799.87
   414.3  805.41   423.9  811.79   452.8  833.51   472.1  847.26   481.8  853.22
   491.4  858.43   510.7  867.25   520.3  871.38     530   875.1   558.9  883.55
#Mann= 3 , 0 , 0
       0     .08       0   331.1    .045       0   360.1      .1       0
Bank Sta=331.1,360.1
XS Rating Curve= 0 ,0
Exp/Cntr=0.3,0.1

Type RM Length L Ch R = 1 ,7481.9  ,104.5,98.3,96
XS GIS Cut Line= 4
     1669358.116      722011.891     1669240.415      722209.441
     1669257.502      722436.583     1669308.718      722522.528
#Sta/Elev= 30
       0   802.2     9.6  800.68    76.6  792.59    95.8  790.55     115  788.95
   134.1  788.14   143.7  788.02   201.2   788.1   258.4  787.35   277.4  786.93
   315.4  785.38   334.4  784.84   343.8  784.41   353.3  783.54   376.3780.3268
   381.8  779.58   391.3  778.83   400.8  779.44   403.3780.2111   410.3  782.37
   419.8  786.93   429.3  791.71   438.8  796.12   448.2   800.1   457.7  803.59
   475.9  810.83   494.1  818.53   512.3  826.59   530.5  834.84   557.8  847.68
#Mann= 3 , 0 , 0
       0      .1       0   376.3    .045       0   403.3      .1       0
Bank Sta=376.3,403.3
XS Rating Curve= 0 ,0
Exp/Cntr=0.3,0.1

Type RM Length L Ch R = 1 ,7383.7  ,40.7,43.7,51.1
XS GIS Cut Line= 6
     1669015.416      722058.709     1669157.012      722379.915
     1669162.741      722413.769      1669155.45      722442.936
     1669115.661      722495.855     1669212.942      722572.294
#Sta/Elev= 30
       0  851.35     9.7  846.87      29  837.29    38.7  833.26    58.1  826.82
    77.4  821.37    96.8  816.42   183.9  795.87   193.6  793.79   203.3   792.2
   251.7  785.74   280.7  783.65   307.5  782.73   316.2  781.76   344.5777.4178
   352.7  776.74   367.3  776.97   371.5777.3783   374.5  777.67   387.1  780.43
   394.3  781.44   401.5  781.82   417.2  782.24   450.3  781.17   483.5  781.55
     493  784.55   512.1  791.59   531.1  799.43   550.1  808.05   607.2  835.75
#Mann= 3 , 0 , 0
       0     .08       0   344.5    .045       0   371.5     .08       0
Bank Sta=344.5,371.5
XS Rating Curve= 0 ,0
Exp/Cntr=0.3,0.1

Type RM Length L Ch R = 1 ,7340    ,261.3,259.1,244.2
XS GIS Cut Line= 6
      1669009.47      722122.294     1669091.534      722309.087
     1669121.724      722409.664     1669115.474      722451.331
     1669064.836      722518.033      1669154.68      722585.308
#Sta/Elev= 30
       0  829.33     9.7   826.2    77.7  806.85   106.9  800.44   126.3  795.92
   145.7  791.72   155.4  789.84   165.2  788.33   174.9  787.26     212  783.68
   235.9   782.5   243.9  781.96   282.7  780.18     289  779.57     300 778.019
   303.6  777.47   310.9  776.79   317.2  776.89     328777.7078   345.7  778.82
   353.5  778.95   437.4  779.19   446.8  779.44   456.1  780.23   465.5  783.28
   493.5  796.03   502.9  800.18   530.9  812.12   540.3  816.26   549.6   820.6
#Mann= 3 , 0 , 0
       0     .08       0     300    .045       0     328     .08       0
Bank Sta=300,328
XS Rating Curve= 0 ,0
Exp/Cntr=0.3,0.1

Type RM Length L Ch R = 1 ,7080.9  ,303.8,302.1,293.4
XS GIS Cut Line= 4
     1668846.185      722130.554     1668867.406       722349.64
      1668931.39      722490.709     1669091.941      722594.257
#Sta/Elev= 30
       0  859.69     9.6     857    19.1  853.83    28.7  850.07    38.3   845.8
    57.4  836.35    86.1  821.15    95.7  816.45   105.3  812.36   114.8  809.16
     134   803.6   143.6  800.35   162.7  791.58   172.3  787.72   181.8  785.11
   191.4   783.5   229.8  779.55   258.8  775.87   280.9 772.467   287.9  771.71
   301.9772.4586   326.6  775.09     346  776.77     375  778.31   413.2  779.27
   489.6  778.84   508.8  779.18   518.3  780.15   527.8  783.46   566.1  804.35
#Mann= 3 , 0 , 0
       0      .1       0   280.9    .045       0   301.9      .1       0
Bank Sta=280.9,301.9
XS Rating Curve= 0 ,0
Exp/Cntr=0.3,0.1

Type RM Length L Ch R = 1 ,6778.8  ,160.8,186.1,214.4
XS GIS Cut Line= 4
     1668686.311       722271.09     1668656.572      722515.686
     1668841.431      722699.026     1668806.753      722773.478
#Sta/Elev= 30
       0  803.53      19  799.41    28.4   796.7    37.9  793.32    56.9  785.85
    66.3  783.08    85.3  779.48    94.8  778.26   132.7  775.85   180.1  773.43
   227.4   771.4     285  769.42   333.2  767.22   347.1766.8968   362.1  766.74
   369.2  766.88   381.4   767.5   400.7  769.33   410.3  770.06     420  770.49
   458.5   771.6   477.8  772.48   506.8  774.21     525  775.01   534.1  775.91
   543.3     779   552.4  784.36   570.6   797.5   579.8  803.05   588.9  806.99
#Mann= 3 , 0 , 0
       0     .08       0   347.1    .045       0   369.2      .1       0
Bank Sta=347.1,369.2
XS Rating Curve= 0 ,0
Exp/Cntr=0.3,0.1

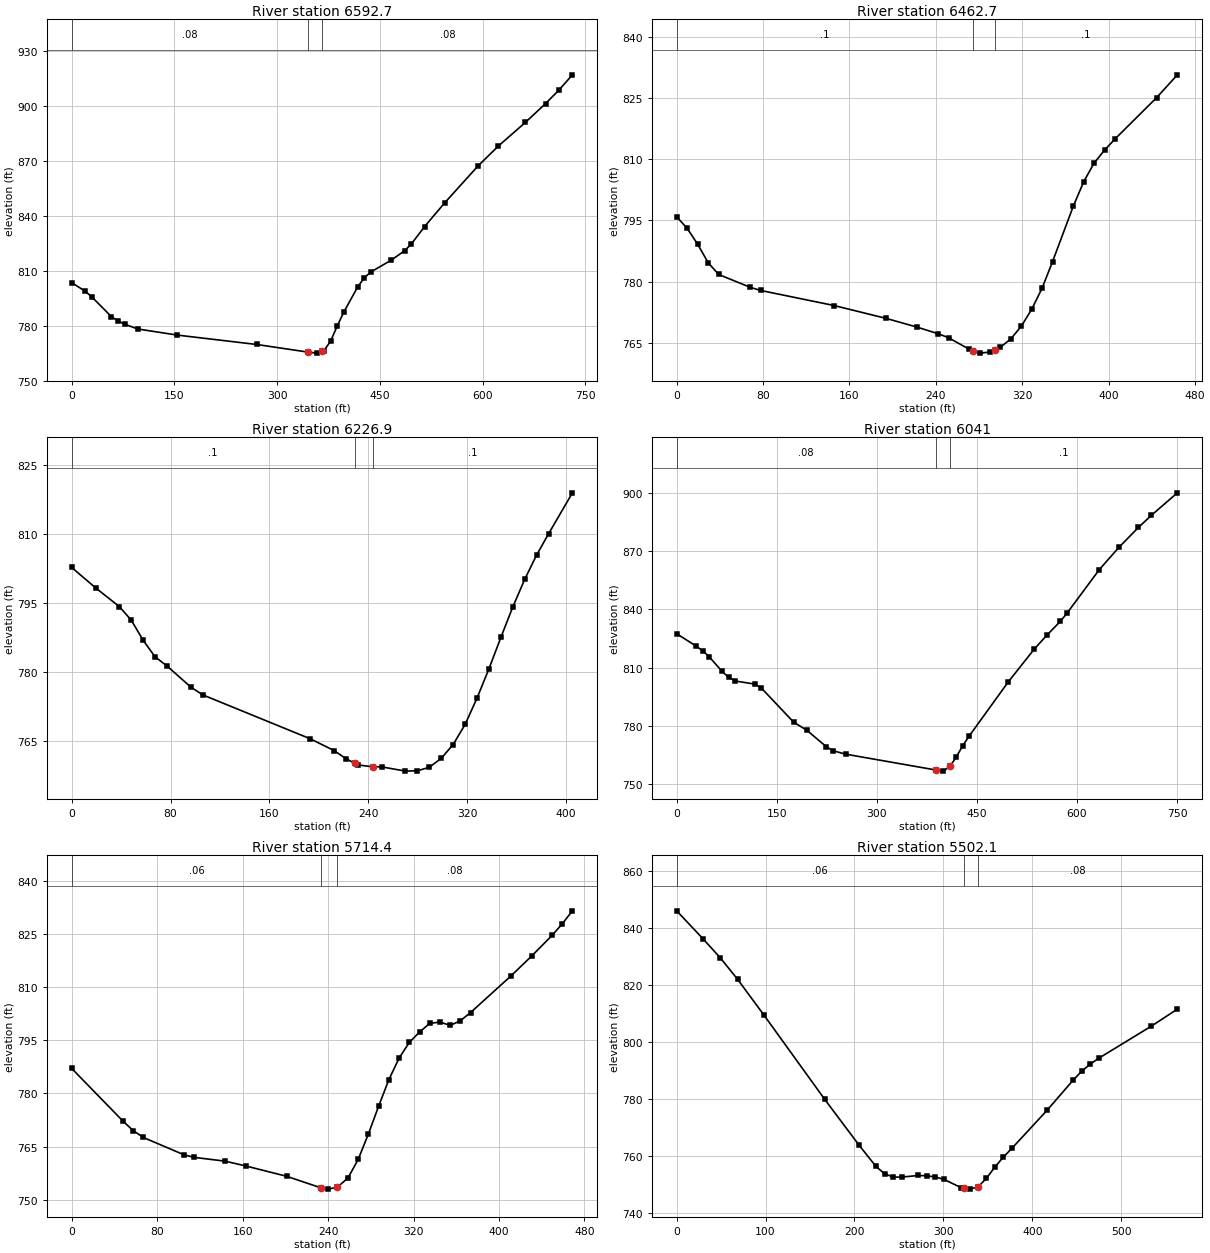
Type RM Length L Ch R = 1 ,6592.7  ,123.7,130,136.4
XS GIS Cut Line= 3
     1668672.526      722269.596     1668647.124      722518.859
     1668407.608      722935.204
#Sta/Elev= 30
       0  803.55    19.3   798.9    28.9   795.9    57.8     785    67.5  782.56
    77.1  780.84    96.4  778.18   154.2  774.84   270.2   769.7     345765.5278
   358.4  764.98     366766.0347   368.2  766.34     378  771.56   387.8  780.03
   397.6  787.68   417.2  801.01     427  806.15   436.8  809.39   466.2  815.75
   485.8  820.93   495.6  824.57   515.2  834.21   544.6  847.22   593.6  867.51
     623  878.28   662.3  891.15   691.7  901.43   711.3  908.84   730.9  917.15
#Mann= 3 , 0 , 0
       0     .08       0     345    .045       0     366     .08       0
Bank Sta=345,366
XS Rating Curve= 0 ,0
Exp/Cntr=0.3,0.1

Type RM Length L Ch R = 1 ,6462.7  ,232.3,235.8,238
XS GIS Cut Line= 3
     1668632.072      722286.134     1668622.243      722412.157
     1668378.083      722644.751
#Sta/Elev= 30
       0  795.85     9.7  793.03    19.4  789.15    29.2  784.59    38.9  781.72
    68.1  778.58    77.8  777.81   145.7  774.12   193.8  770.98   222.8  768.81
     242  767.22   251.7  766.24   270.9   763.4     274763.1011   280.6  762.46
   290.2  762.72   294.3  763.23   299.8  763.91   309.5  765.97   319.1  769.07
   328.7  773.17   338.4   778.4     348  784.86   367.3  798.49   376.9  804.45
   386.5     809   396.2  812.19   405.8  814.89   444.4  825.04   463.6  830.62
#Mann= 3 , 0 , 0
       0      .1       0     274    .045       0   294.3      .1       0
Bank Sta=274,294.3
XS Rating Curve= 0 ,0
Exp/Cntr=0.3,0.1

Type RM Length L Ch R = 1 ,6226.9  ,184,185.9,186
XS GIS Cut Line= 2
     1668562.643      722184.896     1668242.499      722433.057
#Sta/Elev= 30
       0  802.71    19.3  798.29    38.6  794.19    48.2  791.25    57.9  786.84
    67.5  783.27    77.2  781.28    96.4   776.7   106.1  775.01   192.9  765.48
   212.2  762.92   221.8  761.17   228.8  760.17   231.5  759.78     244759.3797
   250.8  759.37     270  758.44   279.7  758.52   289.3  759.27     299  761.22
   308.6  764.22   318.3  768.59   327.9   774.3   337.6   780.7   347.2  787.49
   356.8  794.08   366.5  800.13   376.1   805.4   385.8  810.03   405.1  818.94
#Mann= 3 , 0 , 0
       0      .1       0   228.8    .045       0     244      .1       0
Bank Sta=228.8,244
XS Rating Curve= 0 ,0
Exp/Cntr=0.3,0.1

Type RM Length L Ch R = 1 ,6041    ,317.1,326.6,334.7
XS GIS Cut Line= 2
     1668562.317      722008.663     1667946.857      722438.062
#Sta/Elev= 30
       0  827.48    29.2  821.12      39  818.68    48.7  815.66    68.2  808.07
      78  805.02    87.7  803.17     117   801.6   126.7  799.64   175.4  781.98
   194.9  777.91   224.2  769.43   233.9  767.37   253.4  765.56   388.4757.4312
   399.6  756.85     410759.4429   419.1  764.16   428.8  769.94   438.6     775
     497  802.73     536  819.62   555.5  826.96     575  833.84   584.8  837.94
   633.5  860.47   662.7  871.85     692  882.11   711.5  888.36   750.4  899.91
#Mann= 3 , 0 , 0
       0     .08       0   388.4    .045       0     410      .1       0
Bank Sta=388.4,410
XS Rating Curve= 0 ,0
Exp/Cntr=0.3,0.1

Type RM Length L Ch R = 1 ,5714.4  ,222.8,212.3,201.8
XS GIS Cut Line= 3
     1668313.358      721911.116      1667996.54      721986.537
     1667896.924      722089.223
#Sta/Elev= 30
       0  787.03    47.9  772.19    57.5   769.5      67  767.56   105.4  762.62
   114.9  761.92   143.7  760.86   162.8  759.52   201.2  756.59   233.4  753.33
   239.5  752.97   248.4  753.46   258.6  756.11   268.2  761.38   277.8  768.59
   287.4  776.45   296.9  783.88   306.5  789.97   316.1   794.4   325.7  797.32
   335.2  799.76   344.8  800.11   354.3  799.17   363.8  800.48   373.4  802.81
   411.5  813.23   430.6  818.76   449.7  824.59   459.2  827.85   468.7  831.51
#Mann= 3 , 0 , 0
       0     .06       0   233.4    .045       0   248.4     .08       0
Bank Sta=233.4,248.4
XS Rating Curve= 0 ,0
Exp/Cntr=0.3,0.1

Type RM Length L Ch R = 1 ,5502.1  ,414.2,395.7,376.3
XS GIS Cut Line= 4
     1668222.118      721585.546     1668081.612      721692.271
     1667933.503      721813.141     1667864.129      721996.063
#Sta/Elev= 30
       0  845.93    29.4  836.22      49   829.5    68.6  821.92      98   809.5
   166.6  779.88   205.1   763.9   224.2  756.42   233.8  753.88   243.4  752.71
   252.9  752.69     272  753.26   281.6  753.14   291.1  752.72   300.7  751.89
   319.8  749.01   322.8 748.842   329.4  748.48   338.9  749.25   348.5  752.28
     358  756.25   367.6  759.74   377.4  762.88   416.5  776.04   445.9  786.62
   455.6  789.78   465.4  792.31   475.2   794.4   533.9  805.54   563.2  811.51
#Mann= 3 , 0 , 0
       0     .06       0   322.8    .045       0   338.9     .08       0
Bank Sta=322.8,338.9
XS Rating Curve= 0 ,0
Exp/Cntr=0.3,0.1

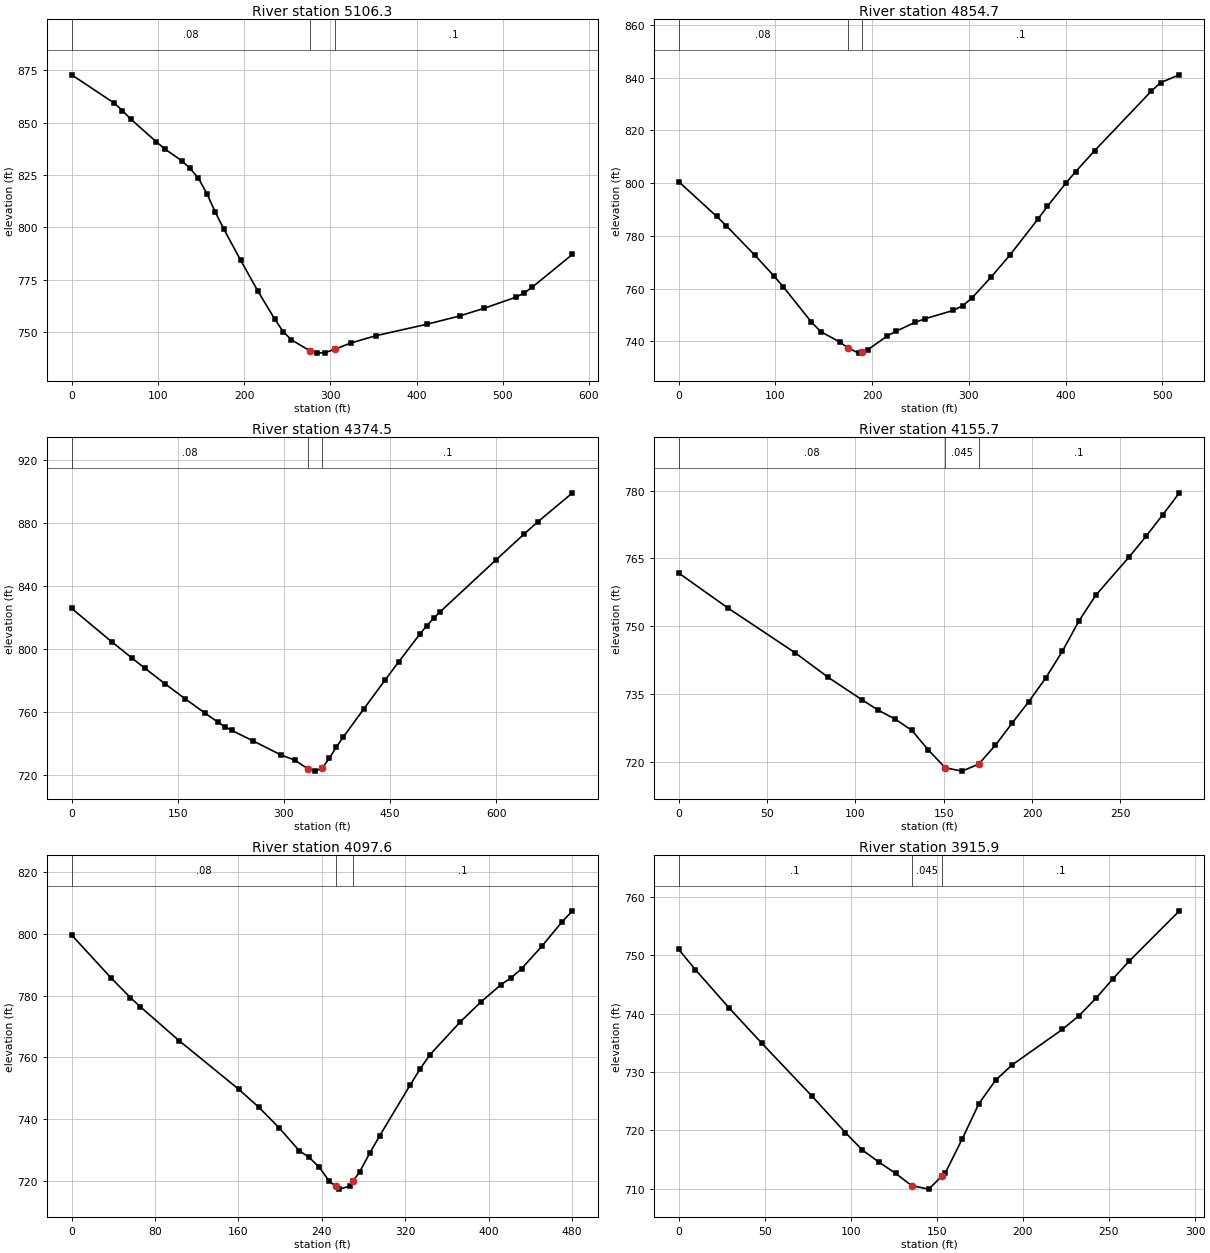
Type RM Length L Ch R = 1 ,5106.3  ,253.9,251.6,249.1
XS GIS Cut Line= 3
     1667656.517      721290.672     1667636.295      721721.514
      1667578.28      721859.294
#Sta/Elev= 30
       0  872.74      49  859.33    58.8  855.72    68.6  851.59      98  840.85
   107.8  837.46   127.4  831.81   137.2  828.18     147  823.41   156.8  816.09
   166.6  807.22   176.4  799.21     196  784.27   215.7  769.79   235.3  756.39
   245.1  750.36   254.9  746.37   276.5741.0767   284.3  740.05   294.1  740.32
   305.5741.9492   323.5  744.86   352.9  748.37   411.7  753.79     450  757.77
     478  761.38   515.4  766.76   524.8  768.75   534.1  771.49   580.8  787.16
#Mann= 3 , 0 , 0
       0     .08       0   276.5    .045       0   305.5      .1       0
Bank Sta=276.5,305.5
XS Rating Curve= 0 ,0
Exp/Cntr=0.3,0.1

Type RM Length L Ch R = 1 ,4854.7  ,462.7,480.2,496.5
XS GIS Cut Line= 4
      1667406.78      721430.093     1667390.667      721536.894
     1667402.256      721731.719     1667314.039      721927.051
#Sta/Elev= 30
       0  800.62    39.3  787.42    49.1  783.93    78.6  772.79    98.2  764.95
     108  760.81   137.3  747.33     147  743.68   166.6  739.81     175  737.56
   186.1  735.59     190  736.13   195.8  736.94   215.4  742.06   225.1  743.96
   244.6  747.28   254.4  748.59   283.7  751.77   293.4  753.51   303.2  756.52
   322.7  764.33   342.2  772.69   371.4  786.45   381.1  791.22   400.6  800.22
   410.3  804.37   429.8   812.3   488.3  834.84     498  838.11   517.5  841.08
#Mann= 3 , 0 , 0
       0     .08       0     175    .045       0     190      .1       0
Bank Sta=175,190
XS Rating Curve= 0 ,0
Exp/Cntr=0.3,0.1

Type RM Length L Ch R = 1 ,4374.5  ,198.2,218.7,238.6
XS GIS Cut Line= 3
     1667252.488      721188.776     1667080.252      721320.305
      1666770.78      721701.893
#Sta/Elev= 30
       0  825.87    56.5  804.78    84.8  794.58   103.6  787.92   131.9  778.14
   160.2  768.68   188.4  759.58   207.3  753.63   216.7  750.83   226.5  748.53
     256  742.04   295.3  733.13     315  729.82   334.6  724.05   344.4  722.77
   354.3  724.73   364.1  730.84   373.9   737.9   383.8  744.27   413.2  762.32
   442.7  780.29   462.4   792.1   491.8  809.37   501.7  814.78   511.5  819.61
   521.3   823.9   599.9  856.66   639.2  872.86   658.9  880.72     708  899.14
#Mann= 3 , 0 , 0
       0     .08       0   334.6    .045       0   354.3      .1       0
Bank Sta=334.6,354.3
XS Rating Curve= 0 ,0
Exp/Cntr=0.3,0.1

Type RM Length L Ch R = 1 ,4155.7  ,58.1,58.1,58.1
XS GIS Cut Line= 3
     1667053.325      721195.179      1666957.49      721234.462
     1666777.673      721233.823
#Sta/Elev= 23
       0  761.79    28.2  753.97    65.9  744.16    84.7  738.71   103.6  733.81
     113  731.46   122.5  729.51     132  727.01   141.4  722.63   150.9  718.74
   160.4     718   169.8  719.55   179.3  723.73   188.8  728.65   198.2  733.38
   207.7  738.56   217.1  744.44   226.6  751.22   236.1  756.88     255  765.35
   264.5  769.89   273.9  774.61   283.4   779.5
#Mann= 3 , 0 , 0
       0     .08       0   150.9    .045       0   169.8      .1       0
Bank Sta=150.9,169.8
XS Rating Curve= 0 ,0
Exp/Cntr=0.3,0.1

Type RM Length L Ch R = 1 ,4097.6  ,192.7,181.7,170.6
XS GIS Cut Line= 4
     1667150.708      721119.505     1667011.384      721176.355
     1666779.111      721175.943     1666701.333      721235.269
#Sta/Elev= 30
       0  799.62    37.6  785.79    56.4  779.34    65.8   776.4   103.4  765.33
   160.2  749.71   179.5  743.87   198.9  737.26   218.2  729.84   227.9   727.6
   237.6  724.43   247.3  719.84   253.5  718.23   256.9  717.34   266.6  718.28
     270719.9073   276.3  722.92     286  728.99   295.6  734.64   324.7  750.99
   334.4   756.3     344  760.93   373.1  771.56   392.5  777.89   412.1  783.58
   421.9  785.83   431.7  788.71   451.2     796   470.8  803.98   480.6  807.46
#Mann= 3 , 0 , 0
       0     .08       0   253.5    .045       0     270      .1       0
Bank Sta=253.5,270
XS Rating Curve= 0 ,0
Exp/Cntr=0.3,0.1

Type RM Length L Ch R = 1 ,3915.9  ,257.6,233.9,209.1
XS GIS Cut Line= 3
     1667006.776       720930.65     1666843.774      721016.182
     1666766.519      721089.971
#Sta/Elev= 23
       0  751.04     9.7  747.57    29.1  741.06    48.4  734.91    77.5  725.86
    96.9  719.61   106.6  716.66   116.3  714.56     126  712.63   135.4 710.515
   145.3  709.92     153712.1662     155  712.75   164.7  718.49   174.4  724.56
   184.1  728.59   193.8  731.24   222.9   737.3   232.6  739.66   242.4  742.64
   252.1  745.92   261.8  749.04   290.9  757.64
#Mann= 3 , 0 , 0
       0      .1       0   135.4    .045       0     153      .1       0
Bank Sta=135.4,153
XS Rating Curve= 0 ,0
Exp/Cntr=0.3,0.1

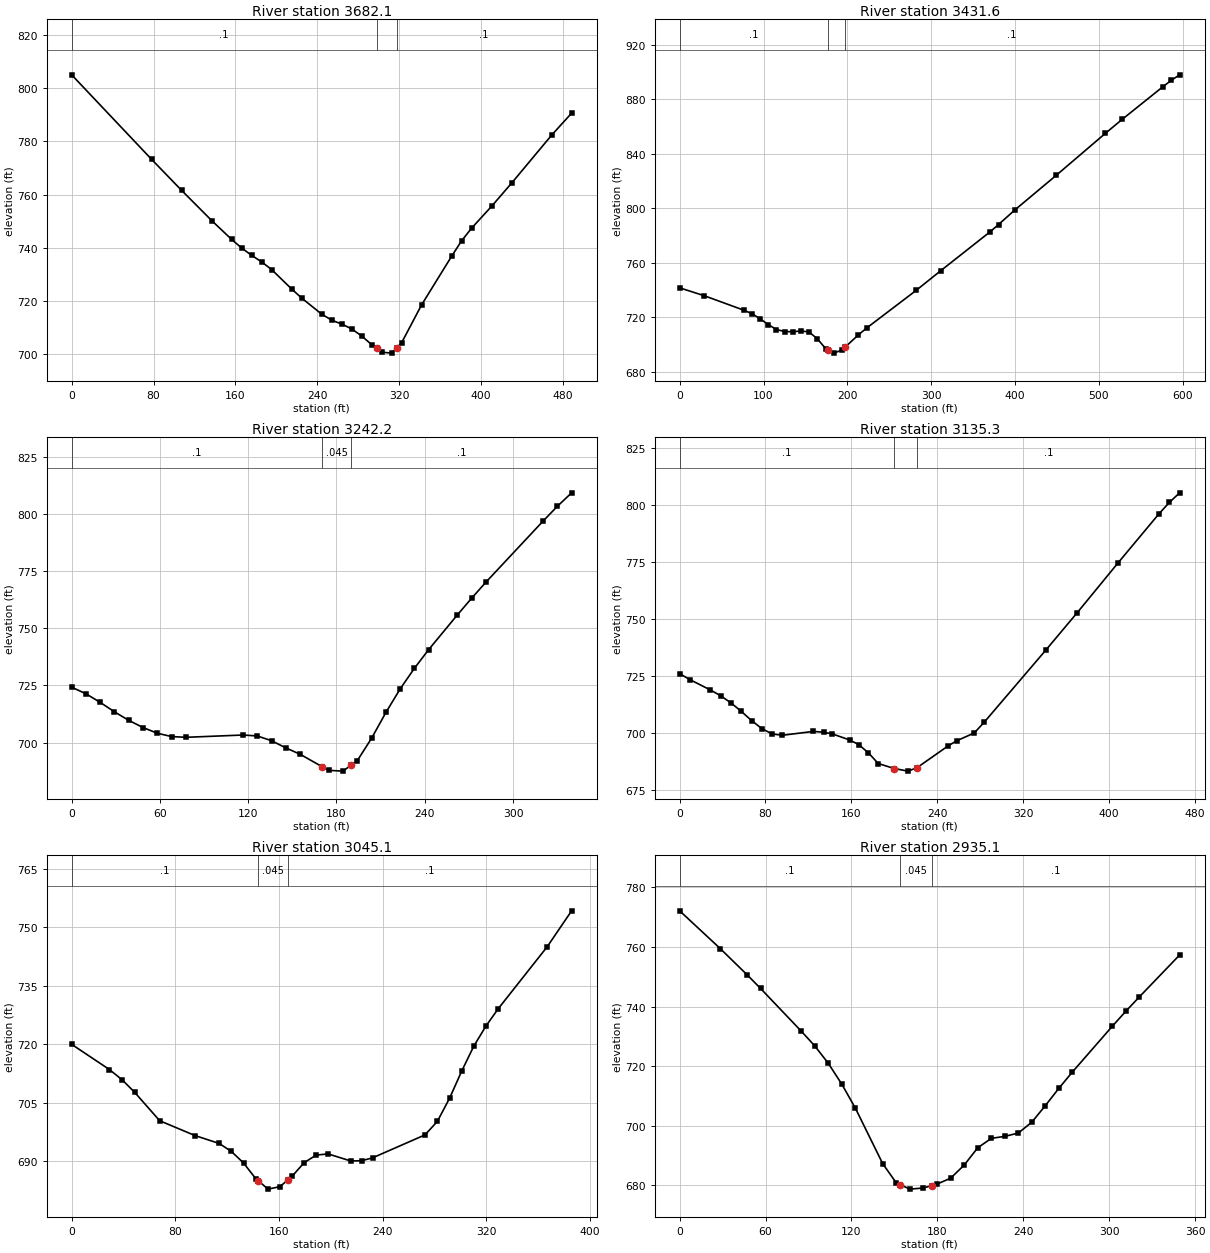
Type RM Length L Ch R = 1 ,3682.1  ,250.1,250.5,250.3
XS GIS Cut Line= 2
     1666667.443      720656.503     1666657.116      721144.772
#Sta/Elev= 30
       0  805.01    78.1  773.26   107.4  761.62   136.8  750.28   156.3   743.2
     166  739.99   175.8  737.23   185.6  734.76   195.4  731.86   214.9  724.59
   224.6  721.21   244.2  715.15     254  712.89   263.7  711.42   273.5  709.62
   283.3  706.94     293  703.71     298702.2574   302.8  700.86   312.6   700.5
   317.5  702.45   322.3  704.37   341.9  718.66   371.2  736.89   380.9  742.66
   390.7  747.43   410.2  755.62   429.8  764.34   468.8  782.32   488.4  790.62
#Mann= 3 , 0 , 0
       0      .1       0     298    .045       0   317.5      .1       0
Bank Sta=298,317.5
XS Rating Curve= 0 ,0
Exp/Cntr=0.3,0.1

Type RM Length L Ch R = 1 ,3431.6  ,157.9,189.4,219.9
XS GIS Cut Line= 3
     1666507.166      720804.366     1666413.172      720900.948
     1666400.488      721362.314
#Sta/Elev= 30
       0  741.64    28.9  735.94      77  725.14    86.6  722.52    96.3  718.79
   105.9   714.6   115.5  711.02   125.1   709.6   134.8  709.38   144.6  710.04
   154.4  709.21   164.2  704.26     174  697.13   177.3695.9993   183.9  693.74
   193.7  696.08     197697.9154   213.3  707.21   223.2  712.23   282.1  739.77
   311.5  754.26   370.4  782.82   380.3  788.05   399.9  798.83     449   824.1
   507.9  855.04   527.6  865.13   576.7  889.33   586.5  893.91   596.3   897.9
#Mann= 3 , 0 , 0
       0      .1       0   177.3    .045       0     197      .1       0
Bank Sta=177.3,197
XS Rating Curve= 0 ,0
Exp/Cntr=0.3,0.1

Type RM Length L Ch R = 1 ,3242.2  ,65,106.9,147.3
XS GIS Cut Line= 2
     1666435.803      720833.882     1666102.841      720901.448
#Sta/Elev= 30
       0  724.19     9.7  721.33    19.4  717.55    29.1  713.44    38.8   709.7
    48.5  706.57    58.2  704.08      68  702.61    77.7   702.3   116.5   703.3
   126.2  702.88   135.9   700.8   145.6  697.66   155.3  694.89     170689.5344
   174.7  687.86   184.4  687.52     190690.1468   194.1  692.07   203.8  701.83
   213.6  713.18   223.3  723.48     233  732.51   242.7  740.66   262.1  755.75
   271.8  763.05   281.5  770.06   320.3  796.72     330  803.18   339.8  809.14
#Mann= 3 , 0 , 0
       0      .1       0     170    .045       0     190      .1       0
Bank Sta=170,190
XS Rating Curve= 0 ,0
Exp/Cntr=0.3,0.1

Type RM Length L Ch R = 1 ,3135.3  ,91,90.1,89.7
XS GIS Cut Line= 6
     1666428.871      720779.759     1666306.388      720834.273
     1666291.197      720805.194     1666274.704      720772.641
      1666250.18      720705.796     1666060.121      720729.065
#Sta/Elev= 30
       0  726.17     9.6  723.57    28.7  719.02    38.3  716.47    47.9  713.35
    57.5  709.64      67  705.64    76.6   702.1    86.2  699.77    95.8  699.19
   124.5  700.87   134.1  700.54   142.3  699.78   158.7  697.08   166.9   695.1
     176  691.45   185.1   686.8     200684.6157   212.8  683.47   221.2  684.96
   250.5  694.62   258.5  696.83   274.6  700.19   284.1  705.03   341.6  736.68
   370.3  752.76   408.6  774.73   446.9  796.32   456.5  801.26     466  805.44
#Mann= 3 , 0 , 0
       0      .1       0     200    .045       0   221.2      .1       0
Bank Sta=200,221.2
XS Rating Curve= 0 ,0
Exp/Cntr=0.3,0.1

Type RM Length L Ch R = 1 ,3045.1  ,145.1,110.1,75.3
XS GIS Cut Line= 6
     1666400.051       720757.19     1666332.169      720756.582
     1666315.676       720724.03     1666280.086      720627.676
     1666274.312      720581.357     1666144.148      720602.908
#Sta/Elev= 30
       0  719.98    29.1  713.52    38.8  710.92    48.5  707.71    67.9  700.38
    95.2  696.57   113.8  694.55   123.2   692.5   132.6  689.54     142  685.53
     144684.9633   151.5  682.83   160.7  683.47     167685.2576     170  686.11
   179.3   689.6   188.6  691.56   197.8  691.87   215.4  690.04   223.8  690.13
   232.1  690.85   272.6  696.75   282.1   700.2   291.5  706.12   300.9  713.11
   310.3  719.56   319.8  724.77   329.2  729.17   366.9  745.04   385.7  754.24
#Mann= 3 , 0 , 0
       0      .1       0     144    .045       0     167      .1       0
Bank Sta=144,167
XS Rating Curve= 0 ,0
Exp/Cntr=0.3,0.1

Type RM Length L Ch R = 1 ,2935.1  ,230.2,216.5,202.5
XS GIS Cut Line= 4
     1666487.204      720553.602     1666414.982       720575.13
      1666253.87      720567.509     1666142.065      720579.991
#Sta/Elev= 30
       0  772.16    28.3  759.51    47.1  750.69    56.5  746.11    84.8  731.84
    94.3  726.86   103.8  720.99   113.3  713.94   122.8  705.86   141.8  687.31
   151.3  680.85     154680.2507   160.8  678.75   170.2  679.13     176679.9307
   179.7  680.44   189.2   682.4   198.7   686.8   208.2  692.63   217.7  695.79
   227.2  696.47   236.6  697.58     246  701.24   255.4  706.77   264.8  712.55
   274.2     718   302.3  733.48   311.6  738.44     321  743.23   349.2  757.33
#Mann= 3 , 0 , 0
       0      .1       0     154    .045       0     176      .1       0
Bank Sta=154,176
XS Rating Curve= 0 ,0
Exp/Cntr=0.3,0.1

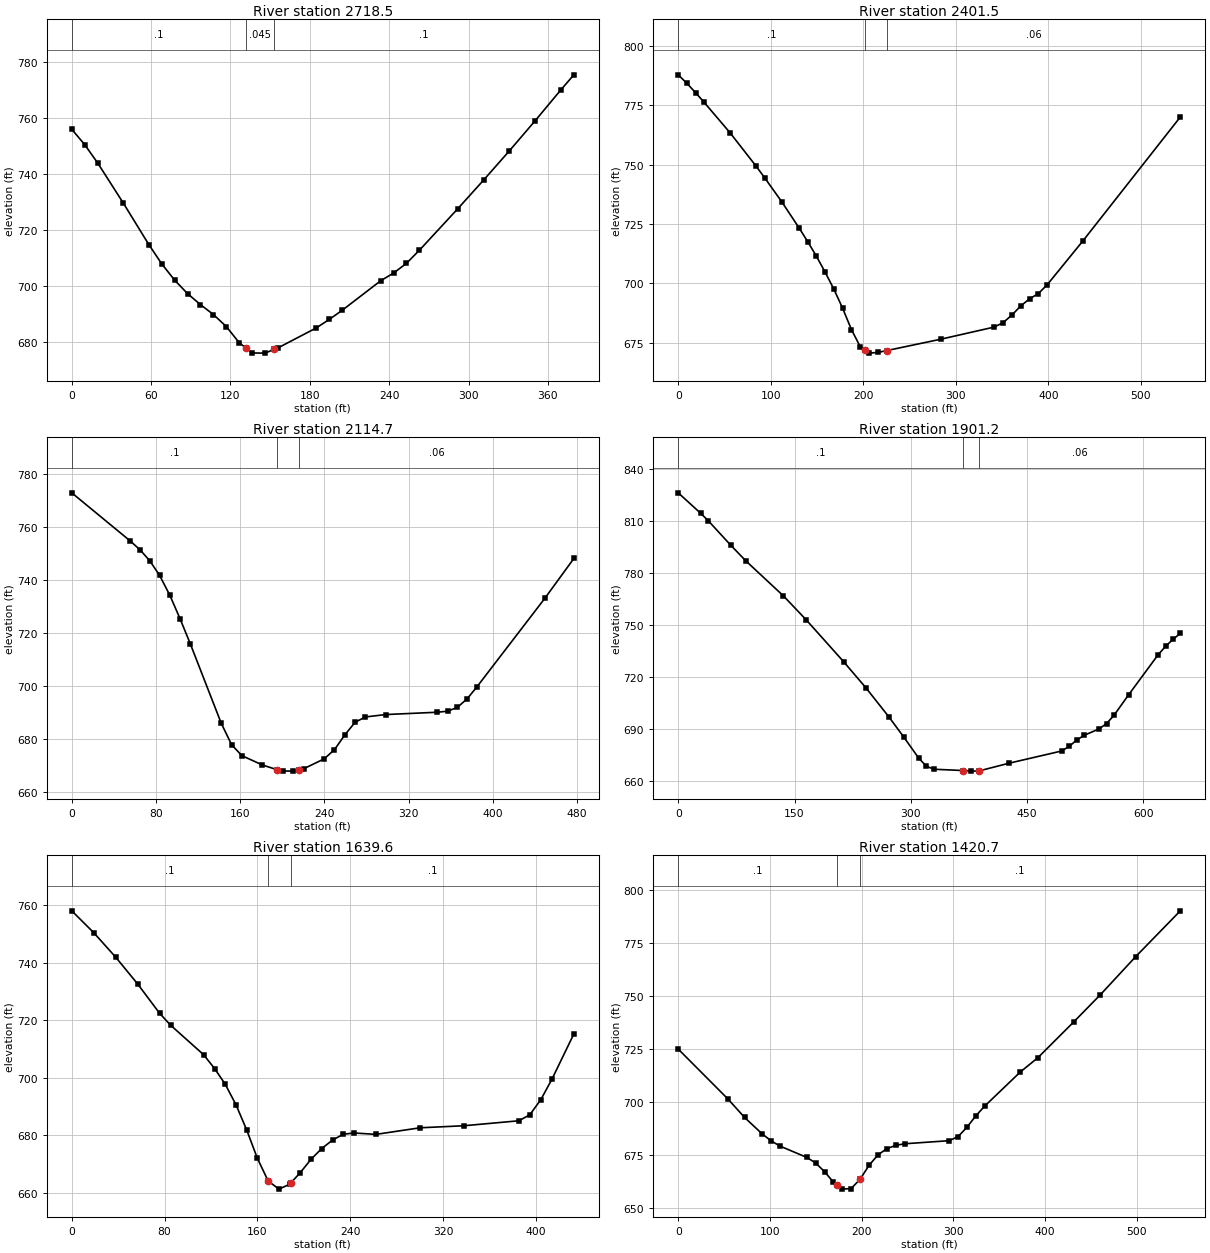
Type RM Length L Ch R = 1 ,2718.5  ,328.9,317,303.6
XS GIS Cut Line= 2
     1666391.156      720291.572     1666070.725      720495.036
#Sta/Elev= 30
       0     756     9.7  750.58    19.5  744.05    38.9  729.73    58.4  714.77
    68.1  707.94    77.9  702.11    87.6  697.34    97.3  693.45   107.1  689.91
   116.8  685.64   126.5  679.91   131.9  677.87   136.3   676.2     146  676.14
     153677.4537   155.7  677.96   184.9  685.14   194.6  688.14   204.4   691.4
   233.6  701.98   243.3   704.7     253  708.16   262.8  712.84     292  727.74
   311.4   737.9   330.9  748.34   350.4  759.09   369.8  770.08   379.6  775.44
#Mann= 3 , 0 , 0
       0      .1       0   131.9    .045       0     153      .1       0
Bank Sta=131.9,153
XS Rating Curve= 0 ,0
Exp/Cntr=0.3,0.1

Type RM Length L Ch R = 1 ,2401.5  ,299.6,286.9,274
XS GIS Cut Line= 4
     1666146.544      719952.982     1666078.341      720106.466
     1665981.649      720305.622     1665962.696      720457.812
#Sta/Elev= 30
       0   787.9     9.3  784.34    18.7  780.41      28  776.31      56  763.49
      84   749.5    93.3  744.59     112  734.36   130.6  723.41     140  717.59
   149.3  711.51   158.6  704.89     168  697.78   177.6  689.65   187.2  680.59
   196.8   673.3     202671.8823   206.5  670.65   216.1  670.96   225.7  671.75
   283.5  676.49   341.2   681.6   350.8  683.39   360.5  686.61   370.1  690.49
   379.7  693.51   389.3  695.76   398.9  699.49   437.3  717.88   542.7  770.13
#Mann= 3 , 0 , 0
       0      .1       0     202    .045       0   225.7     .06       0
Bank Sta=202,225.7
XS Rating Curve= 0 ,0
Exp/Cntr=0.3,0.1

Type RM Length L Ch R = 1 ,2114.7  ,202.6,213.5,223
XS GIS Cut Line= 4
     1665752.205      719959.339     1665766.133      720041.572
     1665811.817      720311.298     1665835.219       720428.84
#Sta/Elev= 30
       0  772.77    55.6  754.59    64.9  751.25    74.1  747.13    83.4  741.64
    93.2  734.09   102.9  725.22   112.7   715.7     142  685.81   151.8  677.78
   161.6  673.64   181.1  670.13     195668.3531   200.6  667.88   210.4  667.82
     216668.3304   220.2  668.71   239.7  672.44   249.5  675.92   259.3  681.48
     269  686.22   278.8  688.25   298.4  689.16   347.2  690.03     357  690.42
   366.2  691.88   375.4  695.06   384.6  699.52   449.2  732.96   476.8  748.01
#Mann= 3 , 0 , 0
       0      .1       0     195    .045       0     216     .06       0
Bank Sta=195,216
XS Rating Curve= 0 ,0
Exp/Cntr=0.3,0.1

Type RM Length L Ch R = 1 ,1901.2  ,271.5,261.6,251.1
XS GIS Cut Line= 3
     1665708.599      719818.935     1665529.309      720331.409
     1665525.413      720436.111
#Sta/Elev= 30
       0  826.04    29.1   814.2    38.8  809.95    67.9  795.81    87.3  786.84
   135.7  766.72   164.8  753.08   213.3  728.89   242.4  713.67   271.5  697.24
   290.9  685.53   310.2  673.38   319.9   668.8   329.6  666.97     367 666.239
   378.1  665.88   387.8  665.97   426.6  670.42   494.5  677.45   504.2  680.08
   513.8  683.67   523.5  686.46   542.9  690.17   552.5  693.24     562  697.91
     581   709.8   619.1  732.87   628.7  737.69   638.2  741.72   647.7  745.11
#Mann= 3 , 0 , 0
       0      .1       0     367    .045       0   387.8     .06       0
Bank Sta=367,387.8
XS Rating Curve= 0 ,0
Exp/Cntr=0.3,0.1

Type RM Length L Ch R = 1 ,1639.6  ,209,218.9,228.3
XS GIS Cut Line= 4
      1665438.13      719859.895     1665382.016      719969.417
     1665394.263      720089.021     1665292.297      720248.784
#Sta/Elev= 30
       0  758.04    18.9  750.45    37.9   741.9    56.8  732.59    75.7   722.4
    85.2  718.24   113.6     708   123.1  703.18   132.3   697.7   141.6  690.53
   150.8  681.78     160  671.92   169.3  664.04   178.6  661.21   187.8  662.91
     189663.4382     197  666.96   206.3  671.62   215.5  675.34   224.8  678.28
     234   680.3   243.3  680.75   262.2  680.26   300.2  682.55     338  683.26
   385.4  684.99   394.9  687.09   404.4  692.39   413.9  699.44   432.8   715.2
#Mann= 3 , 0 , 0
       0      .1       0   169.3    .045       0     189      .1       0
Bank Sta=169.3,189
XS Rating Curve= 0 ,0
Exp/Cntr=0.3,0.1

Type RM Length L Ch R = 1 ,1420.7  ,227.4,229.4,231.1
XS GIS Cut Line= 3
     1665277.583      719859.939     1665211.921      719890.135
     1665061.779      720340.835
#Sta/Elev= 30
       0  724.81    54.2  701.28    72.3   692.6    91.7  684.76   101.4  681.52
     111  679.08   140.1  673.77   149.8  671.13   159.5  667.04   169.2  662.08
     173660.8008   178.9  658.81   188.6   659.1   198.3  663.52     208  670.01
   217.7  674.96   227.4  677.88   237.1  679.44   246.8  680.19   295.3  681.64
     305  683.55   314.6  687.92   324.3   693.3     334  697.92   372.8  713.98
   392.2  720.82     431  737.56   460.1  750.41   498.8  768.45   547.3  789.98
#Mann= 3 , 0 , 0
       0      .1       0     173    .045       0   198.3      .1       0
Bank Sta=173,198.3
XS Rating Curve= 0 ,0
Exp/Cntr=0.3,0.1

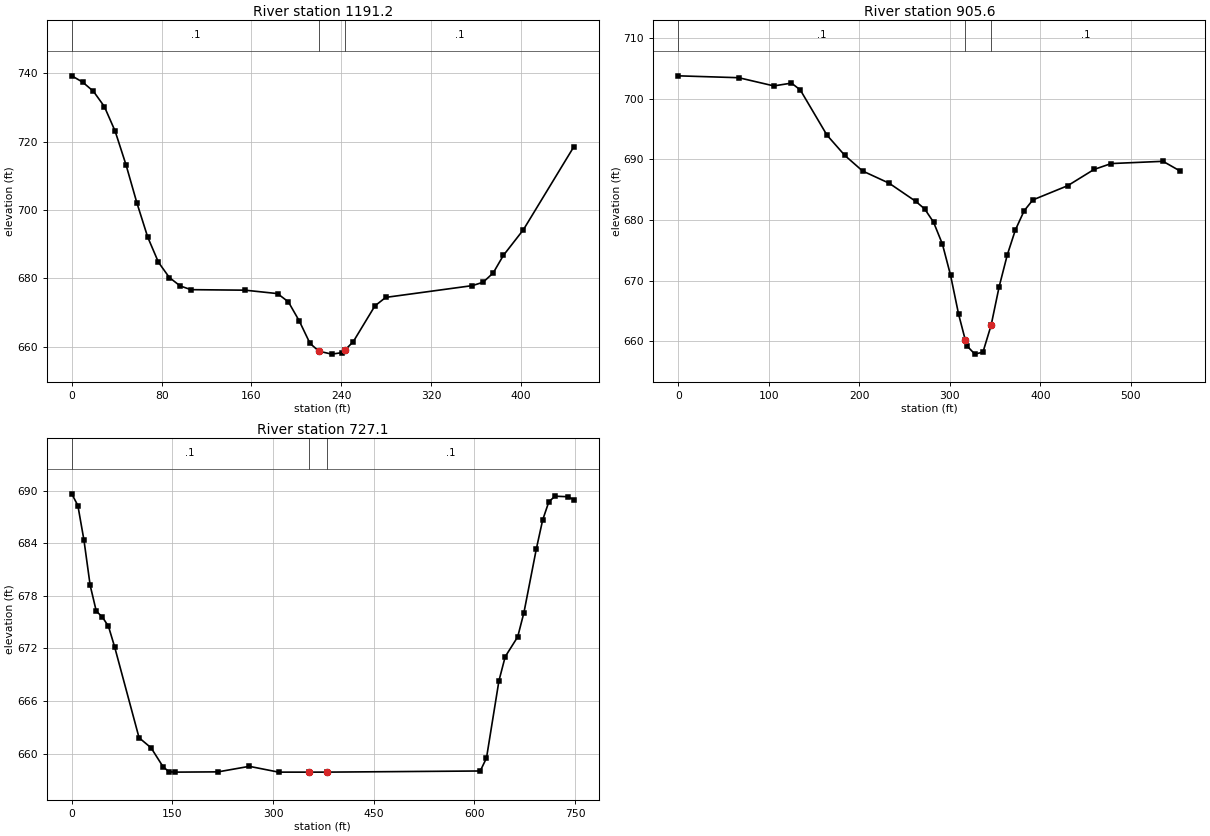
Type RM Length L Ch R = 1 ,1191.2  ,293.7,285.6,277.4
XS GIS Cut Line= 4
     1665033.182      719710.199     1665022.584      719776.961
     1664905.142      720051.531     1664892.123      720131.206
#Sta/Elev= 30
       0  739.19     9.7  737.35    19.3  734.66      29  730.22    38.6  723.03
    48.3  713.19    57.9  702.16    67.6  692.09    77.2  684.71    86.9  680.27
    96.5  677.82   106.1  676.73   154.3  676.58   183.2  675.58   192.8  673.18
   202.5  667.62   212.1  661.04     220658.7606   231.4   657.9     241  658.35
     243659.0125   250.6  661.53   269.9  671.99   279.5  674.47   356.6  677.91
   366.2  678.89   375.2  681.61   384.2  686.71   402.1  694.25     447  718.48
#Mann= 3 , 0 , 0
       0      .1       0     220    .045       0     243      .1       0
Bank Sta=220,243
XS Rating Curve= 0 ,0
Exp/Cntr=0.3,0.1

Type RM Length L Ch R = 1 ,905.6   ,176.9,178.5,179.9
XS GIS Cut Line= 6
     1664685.526      719526.475     1664688.998      719593.142
     1664688.304      719661.198     1664688.998      719720.225
      1664679.97      719985.503     1664674.415      720080.642
#Sta/Elev= 30
       0  703.76    66.8  703.45   105.6   702.1   125.1  702.56   134.8  701.44
   164.3  693.99     184  690.65   203.6  688.09     233  686.07   262.4  683.08
   272.2  681.84     282  679.66   291.8  676.05   300.8  670.92   309.7  664.49
     317660.2966   318.7  659.32   327.6  657.92   336.6  658.25   345.6  662.67
   354.5  669.03   363.5  674.28   372.4  678.37   382.1  681.53   391.7  683.32
   430.3  685.67   459.3  688.34   478.3  689.31   535.5  689.68   554.6  688.06
#Mann= 3 , 0 , 0
       0      .1       0     317    .045       0   345.6      .1       0
Bank Sta=317,345.6
XS Rating Curve= 0 ,0
Exp/Cntr=0.3,0.1

Type RM Length L Ch R = 1 ,727.1   ,729.4,727.1,725
XS GIS Cut Line= 6
     1664624.957      719589.648     1664524.697      719593.294
     1664516.016      719757.356     1664486.502       720028.19
     1664482.162      720081.141      1664639.28      720098.763
#Sta/Elev= 30
       0  689.63     9.1  688.29    18.2  684.33    27.4   679.2    36.5  676.26
    45.6  675.58    54.7  674.52    63.8   672.2   100.3  661.82   118.2  660.67
     136  658.52   144.9  657.94   153.8   657.9   218.1  657.93   264.6  658.56
   308.2   657.9   352.9   657.9   380.6   657.9   608.8  658.03   618.1  659.51
   636.7  668.33     646  671.06   664.6  673.32   673.9  676.09   692.5  683.39
   701.8  686.64   711.1  688.74   720.4  689.36     739   689.3   748.3  688.97
#Mann= 3 , 0 , 0
       0      .1       0   352.9    .045       0   380.6      .1       0
Bank Sta=352.9,380.6
XS Rating Curve= 0 ,0
Exp/Cntr=0.3,0.1

Chan Stop Cuts=-1
Use User Specified Reach Order=0
Composite Channel Slope=5